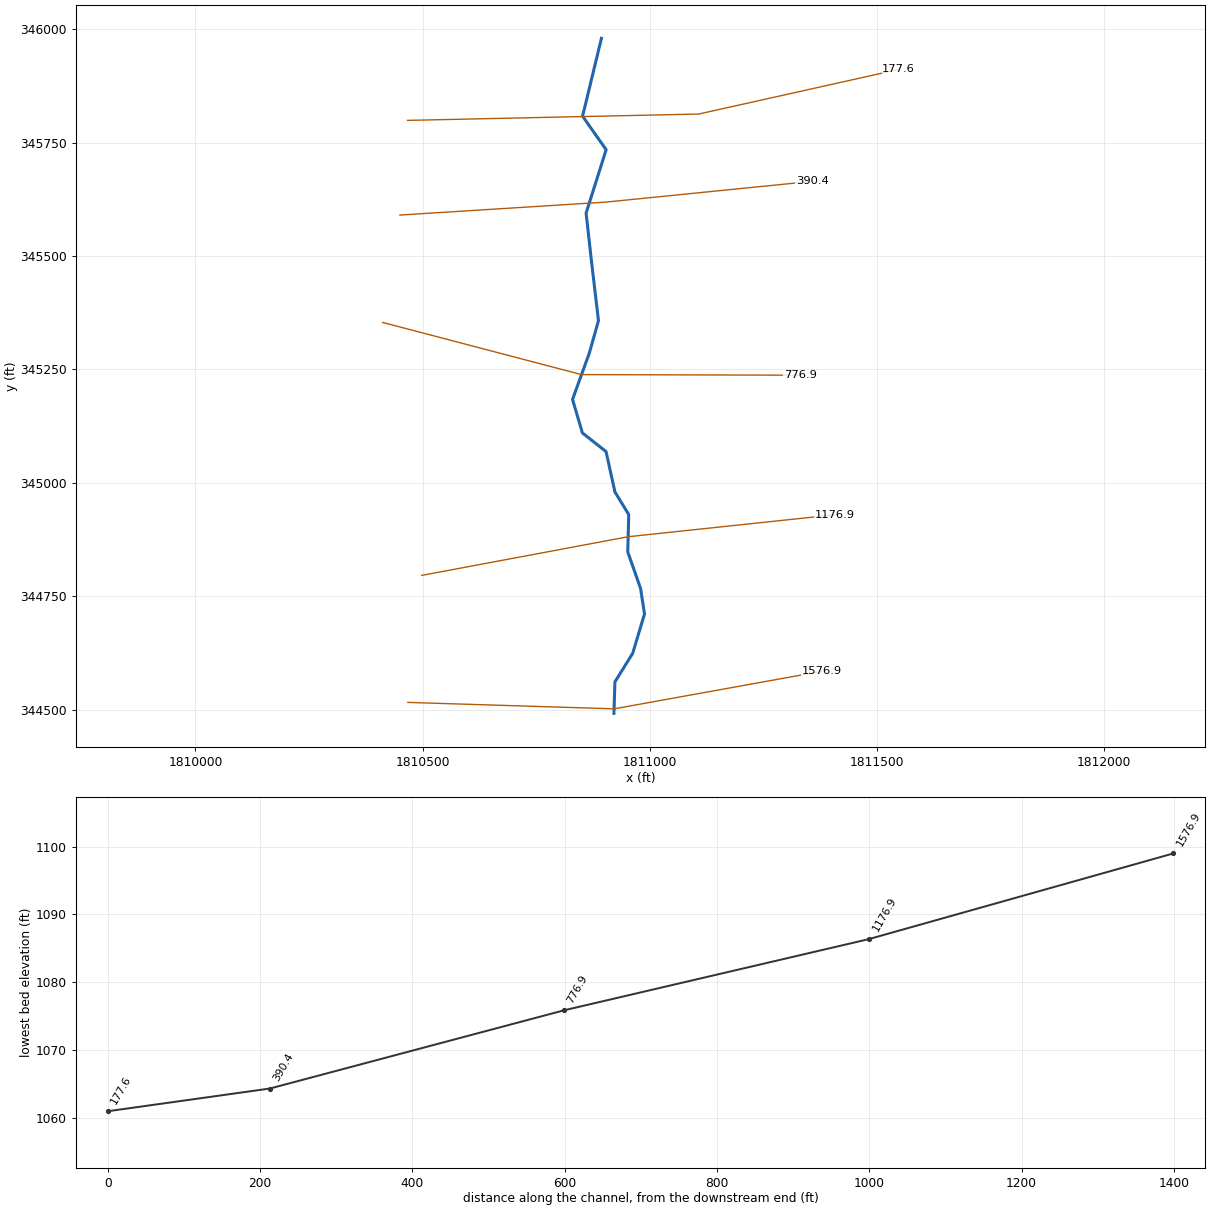
--- LngRn.prj (project) ---

Proj Title=LngRn
Current Plan=p01
Default Exp/Contr=0,0
English Units
Geom File=g01
Flow File=f01
Plan File=p01
BEGIN DESCRIPTION:
END DESCRIPTION:
DSS Export Rating Curves= 0
DSS Export Rating Curve Sorted= 0
DSS Export Volume Flow Curves= 0
DXF OffsetX= 0
DXF OffsetY= 0
DXF ScaleX= 0
DXF ScaleY= 0

--- LngRn.p01 (plan) ---

Plan Title=Floodplain
Program Version=4.00
Geom File=g01
Flow File=f01
K Sum by GR=0
Std Step Tol=0.01
Critical Tol=0.01
Num of Std Step Trials=20
Max Error Tol=0.3
Flow Tol Ratio=0.001
Split Flow NTrial=30
Split Flow Tol=0.02
Split Flow Ratio=0.02
Log Output Level=0
Friction Slope Method=1
Unsteady Friction Slope Method=2
Unsteady Bridges Friction Slope Method=1
Global Log Level=0
CheckData=False
Run HTab=0
Run UNet=0
Run PostProcess=0
UNET Theta=0
UNET Theta Warmup=0
UNET ZTol=0
UNET ZSATol=0
UNET MxIter=0
UNET MaxInSteps=0
UNET DtIC=0
UNET DtMin=0
UNET MaxCRTS=0
UNET WFStab=0
UNET SFStab=0
UNET WFX=0
UNET SFX=0
UNET DSS MLevel=0
UNET DZMax Abort=0
UNET Convert EG Bridges=0
UNET Use Existing IB Tables=0
UNET Froude Limit=0
UNET Froude Power=0
Write IC File=0
Echo Input=False
Echo Output=False
Write Detailed=0

--- LngRn.f01 (steady flow) ---

Flow Title=NFF Regression Equation
Program Version=4.00
Number of Profiles= 1
Profile Names=P100yr
River Rch & RM=LngRn,Main            ,1576.9
717.7026
River Rch & RM=LngRn,Main            ,1176.9
759.9212
River Rch & RM=LngRn,Main            ,177.6
 2704.86
Boundary for River Rch & Prof#=LngRn,Main            , 1
Up Type= 0
Dn Type= 3
Dn Slope=0.010659
DSS Import GetInterval= 0
DSS Import GetPeak= 0
DSS Import FillOption= 0

--- LngRn.g01 (geometry) ---

Geom Title=USGS 3m DEM
Program Version=4.00

River Reach=LngRn     ,Main
Reach XY= 18
     1810920.899      344491.483     1810923.070      344560.927
     1810962.132      344623.861     1810988.174      344710.667
     1810979.493      344767.091     1810951.281      344847.386
     1810953.451      344929.851     1810923.070      344979.764
     1810903.539      345068.740     1810851.455      345109.973
     1810829.754      345183.757     1810866.646      345285.754
     1810886.854      345357.479     1810871.738      345485.961
     1810859.646      345594.793     1810903.709      345734.418
     1810851.912      345808.413     1810893.349      345980.081

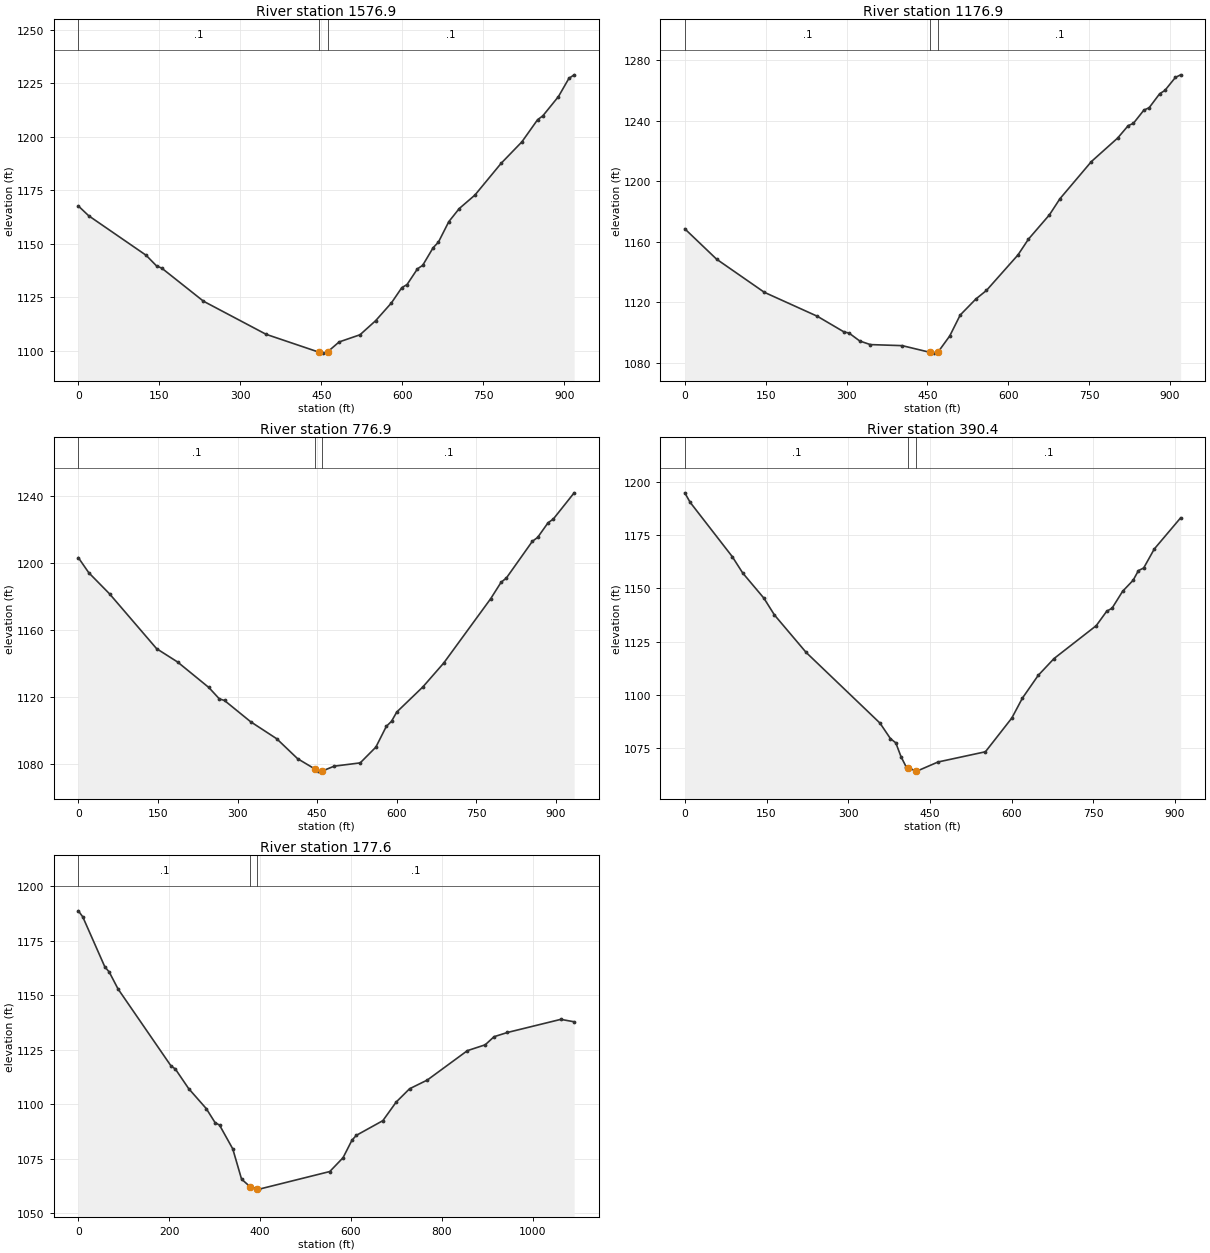
Type RM Length L Ch R = 1 ,1576.9,395.206,400,398.149
XS GIS Cut Line= 3
     1810467.422      344515.660     1810921.212      344501.478
     1811378.036      344584.182
#Sta/Elev= 30
       0 1167.69    19.3 1163.09   125.6 1144.66   144.9 1139.69   154.6 1138.65
   231.8 1123.22   347.8 1107.77   446.5 1099.36   454.0 1098.99   461.5 1099.55
   483.0 1104.21   521.7 1107.56   550.7 1114.15   579.7 1122.38   599.1 1129.55
   608.8 1131.00   628.1 1138.34   637.8 1139.98   657.1 1148.19   666.8 1150.75
   686.1 1160.34   705.5 1166.48   734.5 1172.77   782.9 1187.55   821.5 1197.61
   850.6 1207.96   860.2 1209.73   889.2 1218.75   908.6 1227.26   918.3 1228.90
#Mann= 3 , 0 , 0
       0     0.1       0   446.5   0.045       0   461.5     0.1       0
Bank Sta=   446.5,   461.5
Exp/Cntr=0.3,0.1

Type RM Length L Ch R = 1 ,1176.9,410.043,400,397.835
XS GIS Cut Line= 3
     1810497.828      344795.740     1810952.166      344881.002
     1811407.135      344929.462
#Sta/Elev= 30
       0 1168.50    59.0 1148.43   147.5 1126.55   245.9 1110.70   295.1 1100.40
   304.9 1099.54   324.6 1094.35   344.2 1091.98   403.3 1091.29   454.8 1086.86
   462.3 1086.34   469.8 1087.05   491.5 1097.70   510.9 1111.52   540.1 1122.16
   559.6 1127.77   618.0 1151.21   637.5 1161.67   676.4 1177.73   695.9 1188.37
   754.3 1212.96   803.0 1228.49   822.5 1236.66   832.2 1238.22   851.7 1246.97
   861.4 1248.53   880.9 1257.76   890.6 1259.95   910.1 1268.55   919.8 1270.27
#Mann= 3 , 0 , 0
       0     0.1       0   454.8   0.045       0   469.8     0.1       0
Bank Sta=   454.8,   469.8
Exp/Cntr=0.3,0.1

Type RM Length L Ch R = 1 ,776.9,378.939,386.507,388.039
XS GIS Cut Line= 3
     1810411.960      345353.535     1810849.573      345238.551
     1811331.285      345237.237
#Sta/Elev= 30
       0 1203.17    19.7 1194.16    59.0 1181.51   147.5 1148.87   186.9 1140.95
   245.9 1125.72   265.6 1118.96   275.4 1117.97   324.6 1105.31   373.8 1095.15
   413.1 1083.27     445 1077.25   452.5 1075.84     460 1075.96   482.0 1078.79
   531.1 1080.76   560.6 1090.16   580.3 1102.54   590.1 1105.56   599.9 1111.06
   649.1 1126.05   688.4 1140.29   776.9 1178.66   796.5 1188.47   806.4 1190.98
   855.5 1212.92   865.4 1215.22   885.0 1223.96   894.9 1226.18   934.2 1241.82
#Mann= 3 , 0 , 0
       0     0.1       0     445   0.045       0     460     0.1       0
Bank Sta=     445,     460
Exp/Cntr=0.3,0.1

Type RM Length L Ch R = 1 ,390.4,213.787,212.803,211.121
XS GIS Cut Line= 3
     1810449.919      345590.373     1810904.132      345619.026
     1811356.887      345664.643
#Sta/Elev= 30
       0 1194.78     9.7 1190.37    87.1 1164.88   106.5 1157.13   145.2 1145.39
   164.6 1137.50   222.7 1119.96   358.3 1086.81   377.6 1079.49   387.3 1077.57
   397.0 1071.01   406.7 1066.14     410 1065.75     425 1064.37   426.1 1064.29
   464.8 1068.57   551.9 1073.37   600.3 1089.18   619.7 1098.50   648.8 1109.20
   677.8 1117.07   755.3 1132.50   774.6 1139.29   784.3 1140.67   803.7 1148.61
   823.0 1153.78   832.7 1158.29   842.4 1159.55   861.8 1168.43   910.2 1183.05
#Mann= 3 , 0 , 0
       0     0.1       0     410   0.045       0     425     0.1       0
Bank Sta=     410,     425
Exp/Cntr=0.3,0.1

Type RM Length L Ch R = 1 ,177.6,183.42,177.606,172.332
XS GIS Cut Line= 3
     1810466.737      345799.140     1811107.514      345813.172
     1811547.172      345911.393
#Sta/Elev= 30
       0 1188.73     9.7 1185.99    58.3 1163.02    68.0 1160.64    87.4 1152.86
   203.9 1117.54   213.6 1116.08   242.8 1107.12   281.6 1097.92   301.0 1091.48
   310.8 1090.34   339.9 1079.43   359.3 1065.53   378.3 1062.00   393.3 1061.06
   398.2 1060.94   553.5 1069.02   582.7 1075.37   602.1 1083.33   611.8 1085.62
   670.3 1092.38   699.7 1100.93   729.1 1107.02   768.2 1111.04   856.4 1124.53
   895.6 1127.21   915.1 1130.93   944.5 1132.87  1062.0 1138.89  1091.4 1137.78
#Mann= 3 , 0 , 0
       0     0.1       0   378.3   0.045       0   393.3     0.1       0
Bank Sta=   378.3,   393.3
Exp/Cntr=0.3,0.1